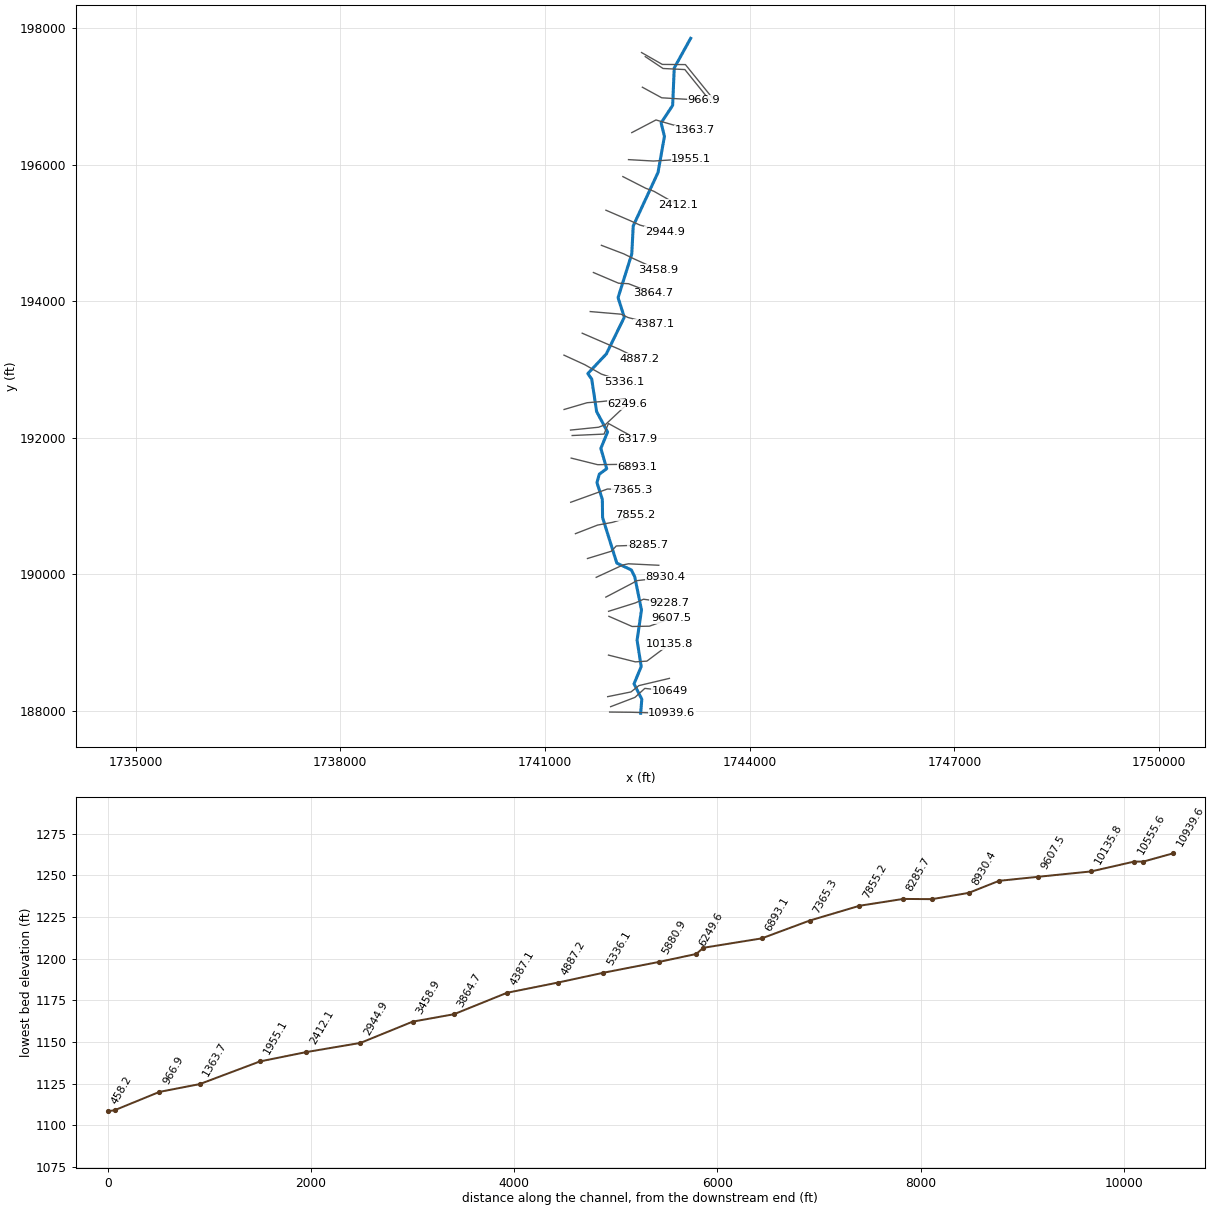
--- BuffaloCr.prj (project) ---

Proj Title=BuffaloCr
Current Plan=p01
Default Exp/Contr=0,0
English Units
Geom File=g01
Flow File=f01
Plan File=p01
BEGIN DESCRIPTION:
END DESCRIPTION:
DSS Export Rating Curves= 0
DSS Export Rating Curve Sorted= 0
DSS Export Volume Flow Curves= 0
DXF OffsetX= 0
DXF OffsetY= 0
DXF ScaleX= 0
DXF ScaleY= 0

--- BuffaloCr.p01 (plan) ---

Plan Title=Floodplain
Program Version=4.00
Geom File=g01
Flow File=f01
K Sum by GR=0
Std Step Tol=0.01
Critical Tol=0.01
Num of Std Step Trials=20
Max Error Tol=0.3
Flow Tol Ratio=0.001
Split Flow NTrial=30
Split Flow Tol=0.02
Split Flow Ratio=0.02
Log Output Level=0
Friction Slope Method=1
Unsteady Friction Slope Method=2
Unsteady Bridges Friction Slope Method=1
Global Log Level=0
CheckData=False
Run HTab=0
Run UNet=0
Run PostProcess=0
UNET Theta=0
UNET Theta Warmup=0
UNET ZTol=0
UNET ZSATol=0
UNET MxIter=0
UNET MaxInSteps=0
UNET DtIC=0
UNET DtMin=0
UNET MaxCRTS=0
UNET WFStab=0
UNET SFStab=0
UNET WFX=0
UNET SFX=0
UNET DSS MLevel=0
UNET DZMax Abort=0
UNET Convert EG Bridges=0
UNET Use Existing IB Tables=0
UNET Froude Limit=0
UNET Froude Power=0
Write IC File=0
Echo Input=False
Echo Output=False
Write Detailed=0

--- BuffaloCr.f01 (steady flow) ---

Flow Title=NFF Regression Equation
Program Version=4.00
Number of Profiles=1
Profile Names=P100yr
River Rch & RM=BuffaloCr,Main      ,10939.6
679.4407
River Rch & RM=BuffaloCr,Main      ,9228.7
734.5323
River Rch & RM=BuffaloCr,Main      ,8930.4
802.2661
River Rch & RM=BuffaloCr,Main      ,8568.3
805.8058
River Rch & RM=BuffaloCr,Main      ,7855.2
911.3229
River Rch & RM=BuffaloCr,Main      ,5880.9
950.7242
River Rch & RM=BuffaloCr,Main      ,4387.1
1038.458
Boundary for River Rch & Prof#=BuffaloCr,Main      ,1
Up Type=0
Dn Type=3
Dn Slope=0.015198

--- BuffaloCr.g01 (geometry) ---

Geom Title=USGS 10m DEM
Program Version=4.00

River Reach=BuffaloCr       ,Main
Reach XY= 30
     1742401.931      187965.993     1742418.772       188171.53
     1742304.628      188396.195     1742409.693      188649.736
     1742349.319      189036.371     1742414.102      189477.822
     1742315.826      189962.649     1742266.688      190064.201
     1742052.119      190165.753     1741843.822      190832.487
     1741840.198      191098.824     1741761.359      191343.623
     1741796.009      191468.485     1741904.143      191547.942
     1741818.456       191844.69     1741916.898      192085.661
      1741756.46      192384.099     1741684.382       192861.12
     1741627.007       192940.84      1741898.78      193228.919
     1742162.098      193766.425     1742070.757      194053.009
     1742271.602      194692.999     1742292.863      195103.538
     1742656.123      195885.989     1742750.335      196414.095
     1742702.019      196612.791     1742870.939      196869.517
     1742894.072      197417.239     1743134.414      197850.981

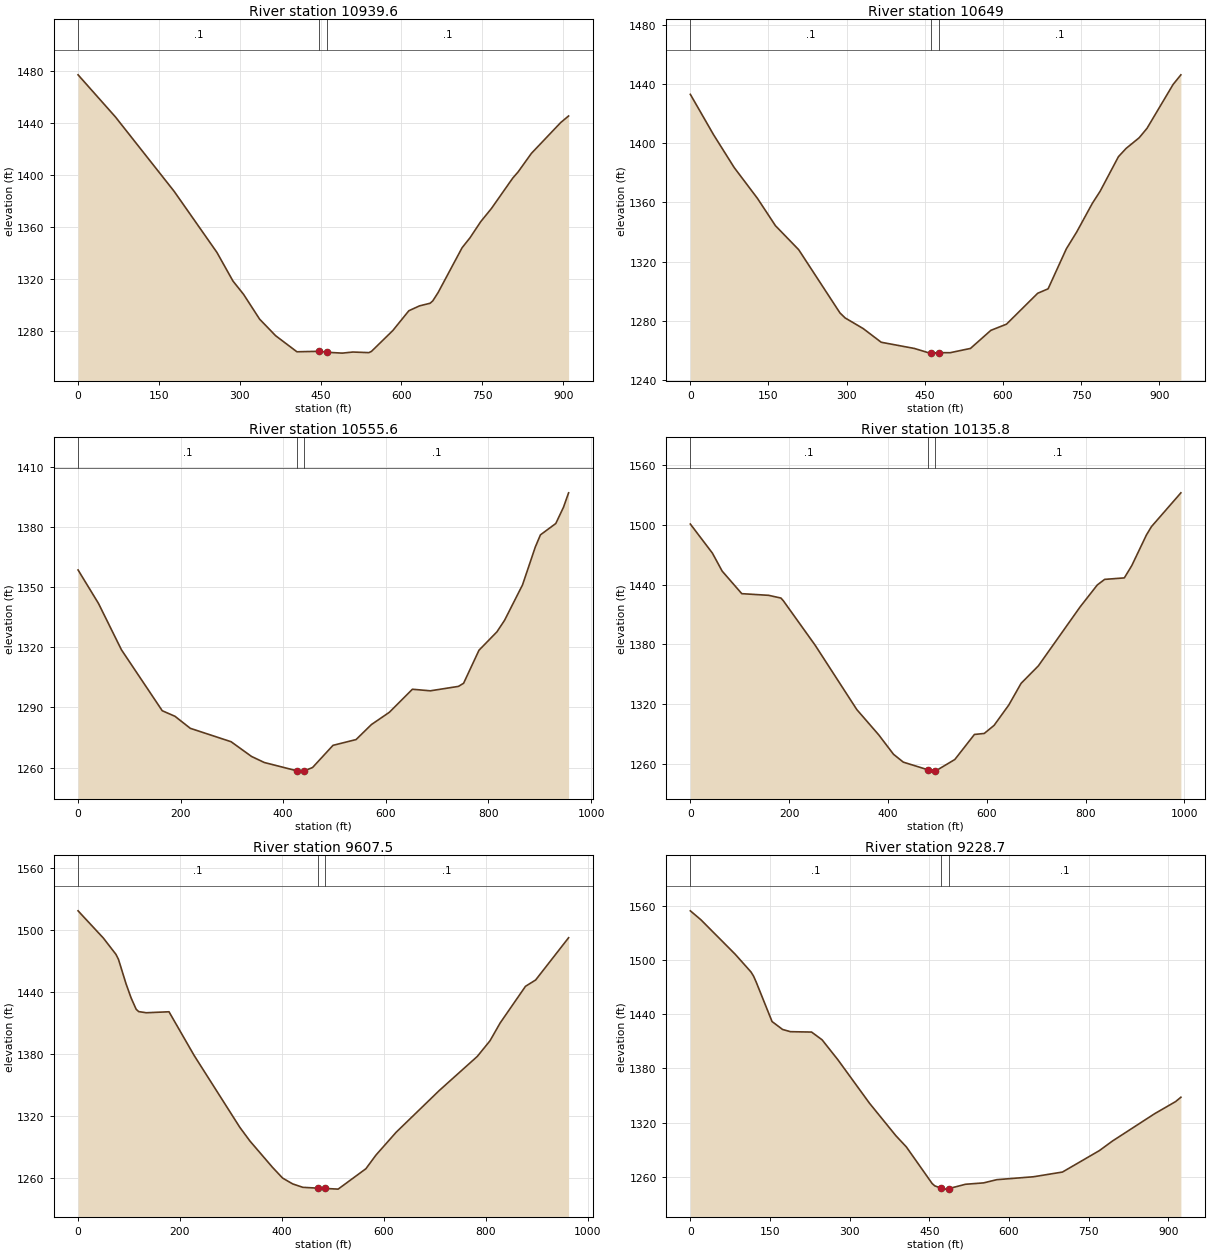
Type RM Length L Ch R = 1 ,10939.6 ,273.2,290.7,308.1
XS GIS Cut Line= 4
     1741947.169      187983.693      1742264.22      187980.549
     1742555.668      187971.913     1742856.973      187964.424
#Sta/Elev= 30
       0  1476.9    69.4 1444.52   178.4 1387.33   257.6 1340.51   287.3 1318.57
   307.2  1308.2   336.8 1289.26   366.5 1276.54     406 1264.19   447.5 1264.56
   462.5 1263.81     490 1263.16   509.8    1264   539.5 1263.54   544.4 1264.54
   583.9 1280.51   613.6 1295.69   633.4 1299.45   653.1 1301.47     658 1303.27
   667.9 1309.66   712.4  1344.1   727.2 1351.81     747 1364.14   766.8 1374.22
   806.3 1397.54   816.2 1402.25   840.9 1416.53   895.2 1440.18     910  1445.3
#Mann= 3 , 0 , 0
       0      .1       0   447.5    .045       0   462.5      .1       0
Bank Sta=447.5,462.5
XS Rating Curve= 0 ,0
Exp/Cntr=0.3,0.1

Type RM Length L Ch R = 1 ,10649   ,94.9,93.3,91.8
XS GIS Cut Line= 4
     1741961.979      188062.586     1742318.192      188198.594
     1742462.836      188330.285     1742825.526      188291.426
#Sta/Elev= 30
       0    1433    44.6 1405.71    84.2 1383.55   128.8 1362.76   163.4 1344.28
     208 1328.09   287.2 1285.41   297.1 1282.03   331.8 1274.83   366.4 1265.59
   430.2  1261.4   459.5 1258.25   461.5 1258.29   476.5 1258.58   498.7 1258.53
   537.8 1261.43   576.9 1273.63   606.9  1277.8   666.8 1298.67   686.8 1301.68
   721.8 1328.68   741.8 1340.11   771.8 1359.45   786.8 1367.64   821.8  1390.9
   836.7 1396.54   861.7 1403.71   876.7 1410.08   926.7 1439.65   941.7 1446.18
#Mann= 3 , 0 , 0
       0      .1       0   461.5    .045       0   476.5      .1       0
Bank Sta=461.5,476.5
XS Rating Curve= 0 ,0
Exp/Cntr=0.3,0.1

Type RM Length L Ch R = 1 ,10555.6 ,433.8,419.9,405.9
XS GIS Cut Line= 4
     1741918.802      188209.389     1742259.903      188278.472
     1742376.481      188371.304     1742823.367      188477.088
#Sta/Elev= 30
       0 1358.63    39.8 1341.93    84.5 1318.81   164.1 1288.36   188.9 1285.59
   218.8 1279.58   298.3 1272.89   338.1 1265.55   362.9 1262.53   426.3 1258.39
   437.4 1258.21   441.3 1258.32   457.3 1260.05     497 1271.08     542 1273.97
   571.9 1281.46   606.9 1287.59   651.8 1299.09   686.7  1298.3   741.6 1300.52
   751.6 1302.08   781.6 1318.56   816.5 1327.72   831.5 1333.52   866.4 1351.14
   891.4  1370.1   901.4 1376.16   931.3 1381.82   946.3 1389.92   956.3 1397.14
#Mann= 3 , 0 , 0
       0      .1       0   426.3    .045       0   441.3      .1       0
Bank Sta=426.3,441.3
XS Rating Curve= 0 ,0
Exp/Cntr=0.3,0.1

Type RM Length L Ch R = 1 ,10135.8 ,529.5,528.2,527
XS GIS Cut Line= 4
     1741930.538      188817.754     1742324.669      188718.881
      1742493.06      188729.676     1742827.624      188980.269
#Sta/Elev= 30
       0 1500.94    44.6 1471.72    64.4  1453.6   104.1  1430.9   158.6 1429.23
   183.4 1426.48   188.3 1423.74   252.7    1379     337 1314.28   381.6 1288.71
   411.3  1269.3   431.2 1261.37   481.1 1253.68   495.7 1252.35   496.1 1252.39
   535.4 1264.03   575.1 1289.24     595 1290.26   614.9 1298.36   644.8 1318.96
   669.6 1340.67   704.5 1358.23   789.1  1417.6   823.9 1439.69   838.8 1445.27
   878.6 1446.77   893.6 1459.08   923.4 1490.01   933.4 1498.28   993.1 1532.36
#Mann= 3 , 0 , 0
       0      .1       0   481.1    .045       0   496.1      .1       0
Bank Sta=481.1,496.1
XS Rating Curve= 0 ,0
Exp/Cntr=0.3,0.1

Type RM Length L Ch R = 1 ,9607.5  ,369.2,378.9,390.9
XS GIS Cut Line= 4
     1741936.478      189385.892     1742277.174      189237.009
     1742529.761      189241.327     1742848.386      189355.444
#Sta/Elev= 30
       0 1518.81    49.6 1492.44    74.4 1476.59    79.3 1471.81    94.2 1448.04
   104.1 1434.41     114 1423.43     119 1421.15   133.8 1420.02   178.5 1420.97
     228 1378.51   317.3 1309.15   337.1 1295.87   381.7 1270.19   401.5 1259.79
   421.3 1254.13   441.2 1250.83   470.2 1250.04   485.2 1249.74   510.5 1249.08
     565 1268.84   584.8  1282.1   624.4  1304.2     709 1344.64   783.7 1377.72
   808.6 1392.86   828.5 1410.09   878.3 1445.66   898.2 1451.78   962.9 1492.73
#Mann= 3 , 0 , 0
       0      .1       0   470.2    .045       0   485.2      .1       0
Bank Sta=470.2,485.2
XS Rating Curve= 0 ,0
Exp/Cntr=0.3,0.1

Type RM Length L Ch R = 1 ,9228.7  ,295.6,298.3,294.4
XS GIS Cut Line= 4
     1741931.755      189459.373     1742324.669      189582.428
     1742443.407        189636.4     1742821.208      189584.587
#Sta/Elev= 30
       0 1554.19    19.8 1544.33    84.3 1506.31   114.1 1486.68   119.1 1481.92
     124 1475.41   153.8 1431.87   173.6 1423.12   188.5 1420.66   228.2 1420.24
     248  1411.7   277.8 1389.61   337.3 1341.59   386.9 1305.74   406.8 1293.23
   455.2 1252.89     460 1250.38   471.9 1247.75   479.4  1246.7   486.9 1247.34
     518 1252.07   552.1 1253.59   576.8 1257.13   646.2 1260.38   700.6 1265.58
     770 1289.24   794.7 1299.85     874 1330.01   913.6 1343.43   923.5 1348.23
#Mann= 3 , 0 , 0
       0      .1       0   471.9    .045       0   486.9      .1       0
Bank Sta=471.9,486.9
XS Rating Curve= 0 ,0
Exp/Cntr=0.3,0.1

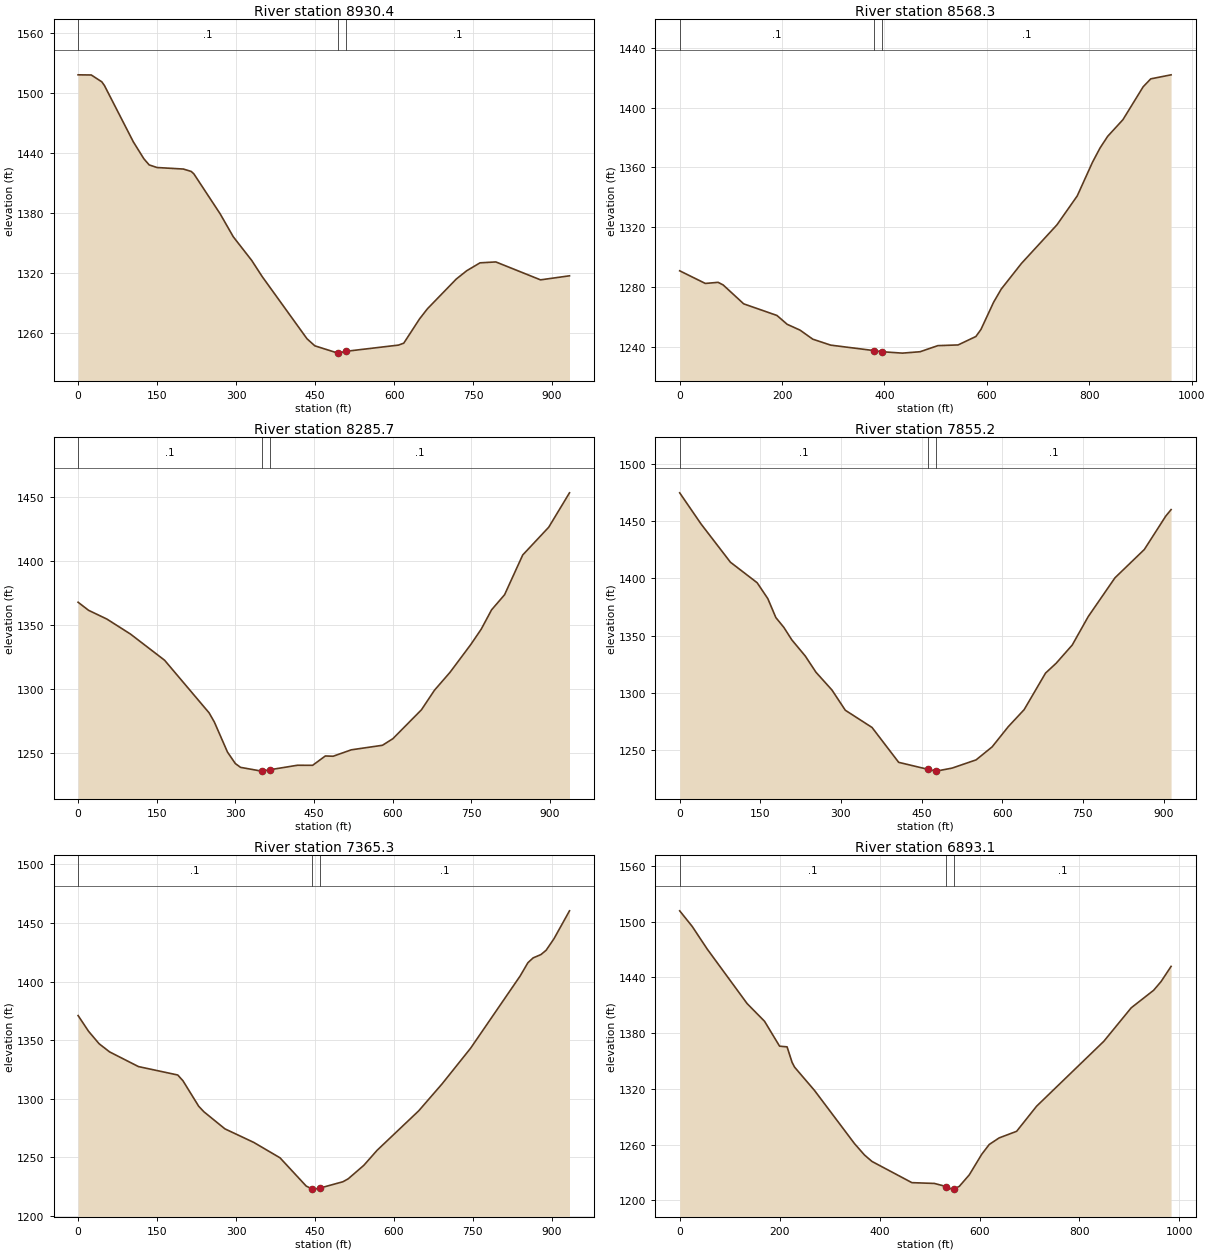
Type RM Length L Ch R = 1 ,8930.4  ,366.7,362,330.1
XS GIS Cut Line= 4
     1741891.876      189667.458     1742285.807      189873.453
     1742339.995      189907.365     1742761.685      189956.969
#Sta/Elev= 30
       0 1518.08      25 1517.92      45 1511.07      50 1507.36   104.9 1450.95
   124.9 1434.04   134.9  1427.9   149.8 1425.28   199.8 1423.76   214.8 1421.35
   219.8 1418.95   269.7 1378.95   294.7 1355.92   329.7 1332.23   349.6 1316.07
   434.6 1253.86   449.5 1246.77     493 1239.52   493.7 1239.46     508 1241.24
   608.4  1247.5   618.4 1249.44   648.3 1273.67   663.3 1283.84   718.3 1313.73
   738.2 1322.04   763.2 1329.85   793.2 1330.76   878.1 1312.82   933.1 1316.87
#Mann= 3 , 0 , 0
       0      .1       0     493    .045       0     508      .1       0
Bank Sta=493,508
XS Rating Curve= 0 ,0
Exp/Cntr=0.3,0.1

Type RM Length L Ch R = 1 ,8568.3  ,285.2,282.6,323.6
XS GIS Cut Line= 4
     1741750.274       189956.86     1742145.159      190139.226
       1742222.7      190155.021     1742667.843      190133.482
#Sta/Elev= 30
       0 1290.81      50 1282.35      75 1283.08      85 1281.32     125 1268.69
     190 1260.91     210 1254.98     235 1251.11     260 1245.03     295 1241.05
   379.4  1237.4   394.4 1236.66     435  1235.7   469.6 1236.64   504.2 1240.71
   543.8 1241.18   578.5 1246.82   588.4 1251.52   613.1 1269.74     628 1278.54
   667.6 1295.77   736.9 1321.59   776.5 1340.94   806.2 1363.41   821.1 1373.06
     836 1380.84   865.7 1391.94   905.3    1414   920.1 1419.29   959.8 1421.99
#Mann= 3 , 0 , 0
       0      .1       0   379.4    .045       0   394.4      .1       0
Bank Sta=379.4,394.4
XS Rating Curve= 0 ,0
Exp/Cntr=0.3,0.1

Type RM Length L Ch R = 1 ,8285.7  ,433,430.5,418.3
XS GIS Cut Line= 4
     1741622.475      190232.562      1741971.41      190338.822
     1742044.643      190416.363     1742509.889      190433.594
#Sta/Elev= 30
       0 1367.71      20 1361.41      55 1354.55    99.9 1342.86   164.9 1322.44
   249.8 1281.33   259.8 1274.17   284.8 1250.74   299.8 1241.76   309.8 1238.77
   349.8 1235.84   350.7 1235.84   365.7 1236.92   418.1 1240.42   447.2 1240.38
   471.4 1247.67   486.3 1247.47   520.9 1252.47   580.4 1256.03   600.2 1261.16
   654.7 1283.74   679.4 1298.94   709.2 1313.01   748.8 1334.72   768.6 1346.64
   788.4 1361.78   813.2 1373.57   847.8 1404.62   897.4 1426.31     937 1453.16
#Mann= 3 , 0 , 0
       0      .1       0   350.7    .045       0   365.7      .1       0
Bank Sta=350.7,365.7
XS Rating Curve= 0 ,0
Exp/Cntr=0.3,0.1

Type RM Length L Ch R = 1 ,7855.2  ,485.8,489.9,493.9
XS GIS Cut Line= 4
     1741446.044      190596.375     1741770.378      190722.219
     1741990.077      190762.426     1742317.518      190863.994
#Sta/Elev= 30
       0 1474.51    39.8 1447.29    94.4 1413.97   144.1 1396.07     164 1382.16
   178.9 1365.67   193.8 1357.09   208.7 1346.16   233.6 1332.14   253.5    1318
   283.3 1302.45   308.1 1284.83   357.8 1269.82   407.4 1239.38   462.5 1233.21
   476.9 1231.72   477.5 1231.74   506.7 1234.36   551.4 1241.54   581.2 1252.87
     611 1270.37   640.8 1285.38   680.6 1317.26   700.4 1325.87   730.2 1341.72
     760 1366.55   809.7 1400.36   864.4  1425.1   904.1 1454.14   914.1 1459.87
#Mann= 3 , 0 , 0
       0      .1       0   462.5    .045       0   477.5      .1       0
Bank Sta=462.5,477.5
XS Rating Curve= 0 ,0
Exp/Cntr=0.3,0.1

Type RM Length L Ch R = 1 ,7365.3  ,479.9,472.2,464.4
XS GIS Cut Line= 3
     1741376.731      191056.042     1741915.408      191250.647
     1742275.678      191233.412
#Sta/Elev= 30
       0 1370.94    19.9  1357.5    39.8 1346.93    59.8 1339.94   114.6 1327.41
   189.3 1320.22   199.2 1315.28   229.1 1293.53   239.1 1288.78   278.9 1274.26
   333.7 1262.69   383.5 1249.57   433.3 1225.44   444.9 1222.87   448.2 1222.84
   459.9  1223.8     503 1229.14     513 1231.62   542.9 1243.22   567.8 1255.92
   646.9 1289.61   691.3 1312.61   745.7 1343.17   839.6 1404.67   854.4 1416.03
   864.3 1420.14   879.1 1422.97     889 1426.66   903.8 1436.42   933.4 1460.31
#Mann= 3 , 0 , 0
       0      .1       0   444.9    .045       0   459.9      .1       0
Bank Sta=444.9,459.9
XS Rating Curve= 0 ,0
Exp/Cntr=0.3,0.1

Type RM Length L Ch R = 1 ,6893.1  ,543.6,575.2,602.7
XS GIS Cut Line= 4
     1741383.821      191703.247     1741771.813      191606.762
     1742076.234       191611.07     1742352.495      191571.394
#Sta/Elev= 30
       0 1511.48      25 1494.74      55 1470.42   134.9 1411.74   169.9 1392.62
   199.9 1365.91   214.9 1365.18   224.9 1348.54   229.9 1343.36   269.9 1318.22
   349.8 1261.12   369.8 1248.86   384.8 1241.93   464.7 1219.11   509.6 1218.28
   533.2 1214.95   544.6 1212.15   548.2 1212.28   559.5  1215.1   579.5 1227.46
   604.4 1249.57   619.4 1260.14   639.4 1267.27   674.3 1274.34   714.2  1301.3
   848.8 1371.16   903.6 1407.15   948.5 1426.03   963.4 1435.43   983.4 1451.72
#Mann= 3 , 0 , 0
       0      .1       0   533.2    .045       0   548.2      .1       0
Bank Sta=533.2,548.2
XS Rating Curve= 0 ,0
Exp/Cntr=0.3,0.1

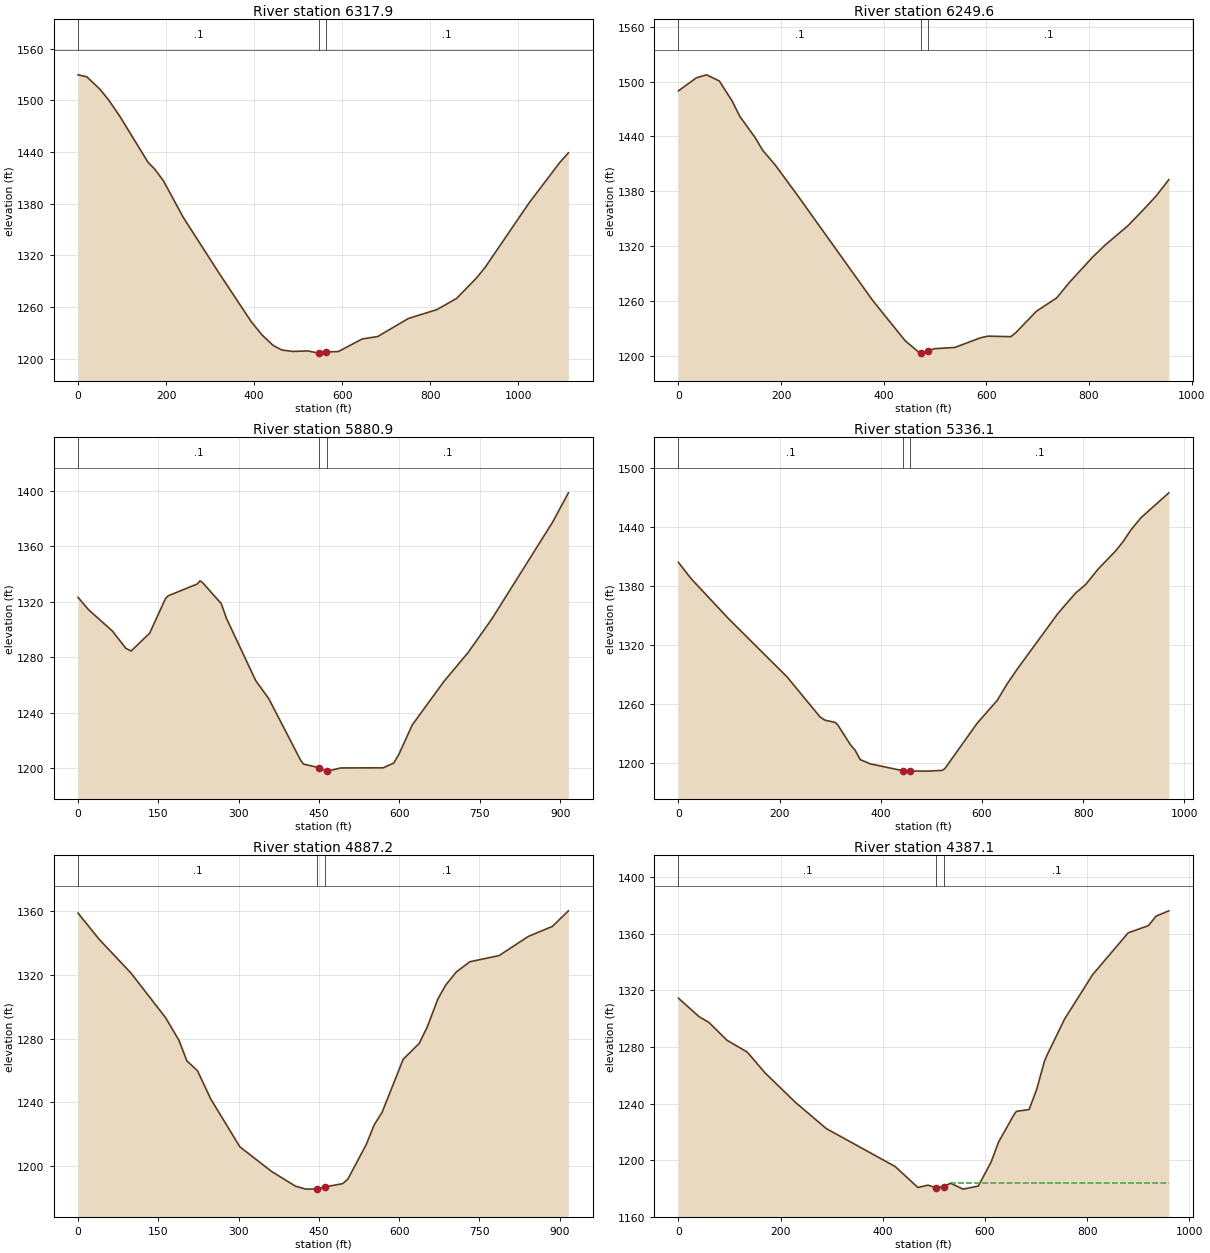
Type RM Length L Ch R = 1 ,6317.9  ,91.8,68.3,48.9
XS GIS Cut Line= 4
     1741398.181      192033.903      1741865.15      192054.777
     1741929.767      192209.859     1742348.906      191980.095
#Sta/Elev= 30
       0 1529.54    19.9 1527.21    49.7 1512.87    69.6  1500.3    94.5 1481.71
   159.1 1427.84     174 1420.19   193.9 1406.49   238.7 1364.24   318.2 1300.94
   392.8 1243.34   417.7 1227.63   442.6 1215.59   462.5 1210.15   487.2 1208.46
   521.8 1209.05   546.5 1206.49   547.9  1206.5   562.9 1207.81     591 1208.31
   645.4 1222.99   680.2  1225.7     750 1246.68   814.7 1256.99   859.5 1269.98
   904.3 1293.49   924.2 1305.95  1023.8 1380.63  1093.5 1427.56  1113.4    1439
#Mann= 3 , 0 , 0
       0      .1       0   547.9    .045       0   562.9      .1       0
Bank Sta=547.9,562.9
XS Rating Curve= 0 ,0
Exp/Cntr=0.3,0.1

Type RM Length L Ch R = 1 ,6249.6  ,375,368.8,362.6
XS GIS Cut Line= 4
     1741374.057       192113.65     1741784.737      192155.293
     1741883.817      192192.627     1742202.597      192491.304
#Sta/Elev= 30
       0 1489.95    34.8  1504.2    54.7 1507.47    79.6 1500.72   104.4 1478.96
   119.4 1462.07   149.2 1438.88   164.1 1424.86     189 1408.41   233.8 1374.12
     378 1260.76   441.7 1216.36   470.5  1202.8   471.6  1202.8   486.6 1205.61
   499.4 1207.67   538.5 1209.03   588.2 1219.53   603.1 1221.37   647.7 1220.81
   657.7  1225.4   697.4  1248.6   737.1 1263.33   761.9 1280.33   806.6 1307.68
   831.4 1321.12   876.1 1342.42   905.9 1359.82   930.7  1374.8   955.5 1392.71
#Mann= 3 , 0 , 0
       0      .1       0   471.6    .045       0   486.6      .1       0
Bank Sta=471.6,486.6
XS Rating Curve= 0 ,0
Exp/Cntr=0.3,0.1

Type RM Length L Ch R = 1 ,5880.9  ,558,544.8,531.6
XS GIS Cut Line= 4
     1741279.599      192415.075     1741616.731      192514.279
     1741829.251       192531.51     1742177.782      192570.229
#Sta/Elev= 30
       0 1323.25    19.8  1314.3    64.4 1298.88    89.1 1286.58      99 1284.59
   133.6 1297.42   163.3 1322.44   168.3 1324.41   222.7 1332.94   227.7  1335.2
   232.6 1333.87   267.3 1318.73   277.2 1307.96   331.6  1263.3   356.4 1249.96
   415.9 1205.55   420.8 1203.11   449.2 1200.52   464.2  1198.1   465.5    1198
   490.3 1200.29   569.6  1200.4   589.3 1203.79   599.2 1210.41   623.9 1231.34
   683.2 1262.78   727.6 1283.25   772.1 1307.53   885.7 1377.41   915.3 1398.62
#Mann= 3 , 0 , 0
       0      .1       0   449.2    .045       0   464.2      .1       0
Bank Sta=449.2,464.2
XS Rating Curve= 0 ,0
Exp/Cntr=0.3,0.1

Type RM Length L Ch R = 1 ,5336.1  ,446.3,448.9,451.4
XS GIS Cut Line= 4
     1741278.101      193210.979     1741582.269      193071.426
     1741826.379      192933.575     1742162.221      192820.497
#Sta/Elev= 30
       0 1403.86      25  1387.3    99.9 1346.13   214.8 1287.33   279.7 1246.76
   289.7 1243.38   309.7 1241.09   314.7 1238.72   339.6 1218.63   349.4 1212.65
   359.2 1203.26   378.9 1198.97     443 1192.04     458 1191.69     492 1191.54
   521.6  1192.3   526.5 1194.03   590.4 1240.22     630 1263.42   649.9 1280.42
   669.9 1295.48   749.8 1351.74   784.7 1372.52   804.7  1381.2   829.6 1397.06
   864.6 1415.78   879.5 1425.34   894.5 1436.99   914.5 1449.42   969.4 1474.66
#Mann= 3 , 0 , 0
       0      .1       0     443    .045       0     458      .1       0
Bank Sta=443,458
XS Rating Curve= 0 ,0
Exp/Cntr=0.3,0.1

Type RM Length L Ch R = 1 ,4887.2  ,501.7,500.2,498.7
XS GIS Cut Line= 4
     1741545.215      193532.326     1741863.714      193394.514
     1742089.157      193296.869     1742380.504       193156.07
#Sta/Elev= 30
       0 1358.63    39.7 1342.16    99.2 1320.96   163.6 1293.07   188.4 1279.02
   203.3 1266.01   223.1 1259.87   247.9 1242.16   302.4 1212.14   361.8 1196.66
     406 1187.52   425.6 1185.61   446.7 1185.76   461.7    1187   494.4 1189.04
   504.3 1191.94   538.7 1213.68   553.4 1225.92   568.2 1233.81   607.6 1267.04
   637.5 1276.96   652.5 1287.23   672.4 1304.82   687.3 1313.67   707.2 1321.88
   732.1 1328.14   786.9 1332.05   841.6 1344.06   886.4 1350.32   916.3 1360.08
#Mann= 3 , 0 , 0
       0      .1       0   446.7    .045       0   461.7      .1       0
Bank Sta=446.7,461.7
XS Rating Curve= 0 ,0
Exp/Cntr=0.3,0.1

Type RM Length L Ch R = 1 ,4387.1  ,512.9,522.3,531.7
XS GIS Cut Line= 4
     1741662.746      193849.324     1742115.004      193810.938
     1742216.956      193762.115     1742597.784      193665.752
#Sta/Elev= 30
       0 1314.49    39.9 1301.55    59.8 1297.29    94.8 1284.79   134.7 1276.35
   169.6 1261.63   229.4  1240.7   289.3 1222.31     424 1195.52   468.6 1180.69
   488.3  1182.3   504.4 1180.55   519.4 1181.28   532.5 1183.69   557.1  1179.5
   586.8 1181.68   611.7 1198.47   626.6 1212.83   656.4 1231.93   661.4 1234.48
   686.3 1235.77   701.2 1250.04   716.1 1269.66   721.1 1273.99   755.9 1299.83
   810.6 1331.11   880.2 1360.68     920  1365.8   934.9 1372.53   959.8 1376.25
#Mann= 3 , 0 , 0
       0      .1       0   504.4    .045       0   519.4      .1       0
#XS Ineff= 2 , 0
                          531.44         1183.64
Permanent Ineff=
       F       F
Bank Sta=504.4,519.4
XS Rating Curve= 0 ,0
Exp/Cntr=0.3,0.1

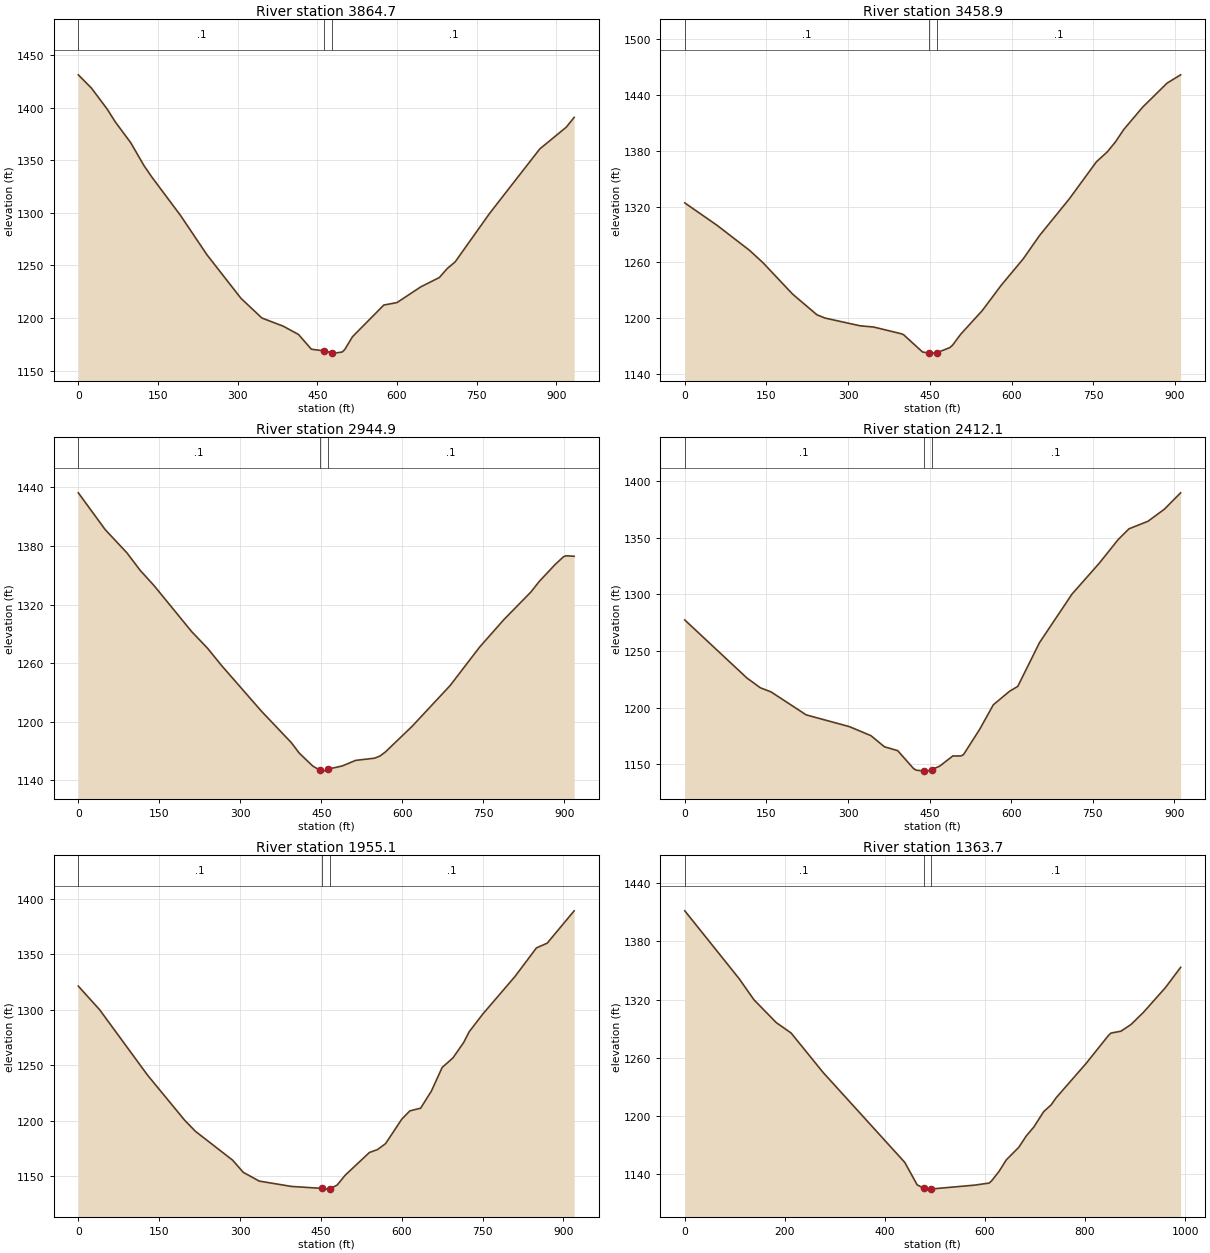
Type RM Length L Ch R = 1 ,3864.7  ,415.3,405.8,396.4
XS GIS Cut Line= 4
     1741709.371      194421.252      1742077.67      194264.696
       1742222.7      194257.517     1742585.008      194117.476
#Sta/Elev= 30
       0 1431.29    24.7 1418.66    54.4 1398.69    69.2  1386.8    98.8 1366.65
   123.5 1345.09   138.3 1334.17   192.7 1297.39   242.1 1260.26   306.3 1218.74
   345.8 1199.98   385.4 1192.37   414.7 1184.36   438.9 1170.33   463.4 1168.72
   478.4 1166.99   482.5 1166.62     497  1167.7   501.8 1170.06   516.4 1182.26
   575.3 1212.34   600.2 1214.71     645 1229.66   679.9 1238.52   694.8 1247.06
   709.7 1253.41   774.5 1299.48   869.1 1360.84   918.9 1381.48   933.8 1390.82
#Mann= 3 , 0 , 0
       0      .1       0   463.4    .045       0   478.4      .1       0
Bank Sta=463.4,478.4
XS Rating Curve= 0 ,0
Exp/Cntr=0.3,0.1

Type RM Length L Ch R = 1 ,3458.9  ,513.2,514,514.7
XS GIS Cut Line= 4
     1741826.648      194819.529     1742155.211      194694.044
     1742298.805      194623.683     1742662.455      194459.487
#Sta/Elev= 30
       0 1323.98    59.4 1299.78   118.9 1272.88   143.7  1259.5   198.2 1225.62
   242.7 1203.47   257.6 1199.94     322 1191.61   346.8 1190.29   396.7 1183.18
   401.7 1182.06   436.7 1163.36   448.3 1162.28   451.6 1162.18   463.3  1162.7
   486.6 1168.09   491.6 1170.63   506.6 1182.46   546.5 1208.13   581.4  1235.5
   621.3 1263.54   651.3 1288.67   706.1 1328.28     756 1368.28     776 1378.98
   790.9 1389.69   805.9 1402.82   840.8 1427.06   885.7 1452.98   910.6 1461.92
#Mann= 3 , 0 , 0
       0      .1       0   448.3    .045       0   463.3      .1       0
Bank Sta=448.3,463.3
XS Rating Curve= 0 ,0
Exp/Cntr=0.3,0.1

Type RM Length L Ch R = 1 ,2944.9  ,531.1,532.8,534.5
XS GIS Cut Line= 4
     1741892.954       195333.66     1742241.368      195183.701
     1742390.706      195116.212     1742752.212      195017.588
#Sta/Elev= 30
       0 1434.35    49.9 1396.57    89.8 1373.01   114.8 1354.78   139.8 1339.61
   209.6 1292.41   239.6 1274.98   264.5 1257.98   339.4 1210.52   394.2 1178.64
   409.1 1167.78   433.9 1154.67   447.5  1150.2   453.8 1149.41   462.5  1151.5
   488.6 1154.71   513.4 1160.41   548.2 1162.64   558.2 1164.79   568.2 1168.91
   618.1  1195.4   688.1 1236.92     743 1276.48     788 1304.66     838 1332.91
     853 1343.44   882.9 1361.09   897.9 1368.76   902.9 1369.91   917.9  1369.4
#Mann= 3 , 0 , 0
       0      .1       0   447.5    .045       0   462.5      .1       0
Bank Sta=447.5,462.5
XS Rating Curve= 0 ,0
Exp/Cntr=0.3,0.1

Type RM Length L Ch R = 1 ,2412.1  ,447.6,457,466.3
XS GIS Cut Line= 4
     1742141.166      195825.889     1742476.863      195654.691
      1742594.61      195611.613     1742950.711      195410.273
#Sta/Elev= 30
       0 1277.26     114 1226.15   138.8 1217.46   158.7 1213.77   223.1 1193.54
   302.5 1183.18   342.1 1175.21   366.9  1165.4   391.3 1161.99   420.2 1146.32
     425 1144.79   438.9 1144.05   444.3 1143.91   453.9 1145.27   468.4 1148.27
   492.6 1157.31   507.2 1157.27   512.2 1158.45   542.1  1180.9   567.1 1202.47
     597 1214.41     612 1218.68   651.9 1257.25   711.7 1300.14   761.6 1327.27
   796.6 1348.28   816.5 1357.74   851.4 1364.39   881.4 1374.99   911.3 1389.46
#Mann= 3 , 0 , 0
       0      .1       0   438.9    .045       0   453.9      .1       0
Bank Sta=438.9,453.9
XS Rating Curve= 0 ,0
Exp/Cntr=0.3,0.1

Type RM Length L Ch R = 1 ,1955.1  ,599.6,591.5,583.4
XS GIS Cut Line= 3
     1742224.224      196074.583     1742588.866      196053.884
     1743142.516      196088.808
#Sta/Elev= 30
       0 1321.19    39.5 1299.96   128.3 1241.07   197.4 1200.32   217.2  1190.4
   286.3 1164.37     306 1153.42   335.6 1145.53   395.2 1140.73   451.8 1138.95
   460.2 1138.28   466.8  1138.6   480.2 1141.92   495.2 1150.85   540.2 1171.32
   555.1 1173.91   570.1 1179.28   600.1 1201.28   615.1 1208.78   635.1  1211.2
   655.1 1226.63   675.1 1247.92   695.1 1256.53   715.1 1270.49   725.1 1279.98
   750.1 1295.82     810 1329.76     850 1355.63     870  1359.9     920 1389.04
#Mann= 3 , 0 , 0
       0      .1       0   451.8    .045       0   466.8      .1       0
Bank Sta=451.8,466.8
XS Rating Curve= 0 ,0
Exp/Cntr=0.3,0.1

Type RM Length L Ch R = 1 ,1363.7  ,391.9,396.8,401.7
XS GIS Cut Line= 4
     1742271.615      196470.088     1742626.201      196655.545
     1742868.876      196585.184     1743197.364      196504.085
#Sta/Elev= 30
       0 1411.42   108.7 1341.48   138.3 1319.77   182.8 1296.27   212.4  1285.6
   276.6 1244.84   439.8 1152.23   464.6 1129.04   477.5 1125.68   484.4 1124.69
   492.5 1124.83   578.5 1128.76   608.2 1130.91   613.2 1133.13   628.1  1142.9
   642.9 1154.96   667.8 1167.84   682.7 1179.54   697.6 1188.56   717.5 1204.57
   732.4  1211.5   742.4 1218.84   802.1 1254.12   846.9 1282.97   851.9 1285.46
   871.8 1287.39   891.7 1294.17   916.5 1306.62   961.3  1332.6   991.2  1353.2
#Mann= 3 , 0 , 0
       0      .1       0   477.5    .045       0   492.5      .1       0
Bank Sta=477.5,492.5
XS Rating Curve= 0 ,0
Exp/Cntr=0.3,0.1

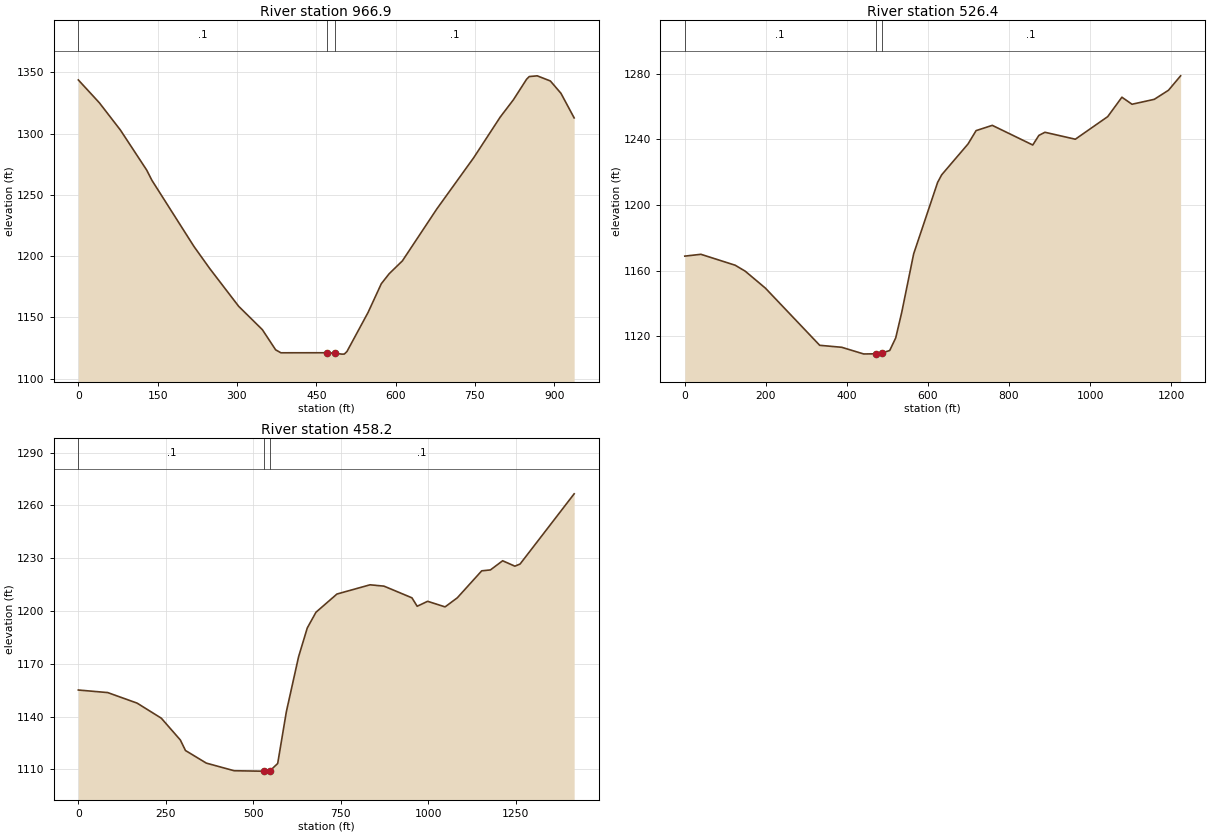
Type RM Length L Ch R = 1 ,966.9   ,440.2,440.5,440.8
XS GIS Cut Line= 3
     1742427.218      197134.717     1742710.922      196980.069
     1743324.396      196943.191
#Sta/Elev= 30
       0 1343.92    39.8 1325.25    79.5 1303.04   129.2 1270.37   139.2 1261.93
   218.7 1207.92   248.6 1189.85   303.2 1159.08   348.1 1139.96   373.1 1123.55
   383.1  1121.1   470.9 1121.14   485.9 1120.78     498 1120.01     503 1120.05
     508 1122.12     548  1154.1     573 1177.51   587.9 1185.68   612.9 1196.19
   677.9 1238.53   747.8 1280.45   797.8 1313.55   822.8 1327.73   847.8 1344.52
   852.8 1346.68   867.8 1347.28   892.7 1343.08   912.7 1333.02   937.7 1312.91
#Mann= 3 , 0 , 0
       0      .1       0   470.9    .045       0   485.9      .1       0
Bank Sta=470.9,485.9
XS Rating Curve= 0 ,0
Exp/Cntr=0.3,0.1

Type RM Length L Ch R = 1 ,526.4   ,67.2,68.2,69.3
XS GIS Cut Line= 4
     1742469.161      197583.382     1742729.589      197409.417
     1743049.805      197393.621     1743420.188      196934.854
#Sta/Elev= 30
       0  1168.8    39.8 1169.91   124.3 1163.25   149.1 1159.62   198.8 1149.29
   332.9  1114.4   387.2 1113.19   441.4 1109.12     471 1109.21     476 1109.02
     486 1109.68   505.6 1111.23   520.4  1118.9   535.2  1134.4   564.7  1170.2
   623.9 1213.82   633.8 1218.39   698.8  1237.2   718.7 1245.35   758.7 1248.57
   858.6 1236.58   873.6 1242.43   888.6 1244.35   963.6 1240.11  1043.5 1253.89
  1078.5 1265.73  1103.5 1261.44  1158.4 1264.44  1193.4 1269.97  1223.4 1278.78
#Mann= 3 , 0 , 0
       0      .1       0     471    .045       0     486      .1       0
Bank Sta=471,486
XS Rating Curve= 0 ,0
Exp/Cntr=0.3,0.1

Type RM Length L Ch R = 1 ,458.2   ,466.5,458.2,449.8
XS GIS Cut Line= 4
     1742414.865       197642.93     1742719.361      197468.932
     1743057.691      197466.515     1743515.645      196901.021
#Sta/Elev= 30
       0 1155.08      84 1153.62   167.9 1147.63   237.1 1139.06   291.4 1126.69
   306.2 1120.68   365.6 1113.53   445.2 1109.19   531.9 1108.91   539.8  1108.4
   546.9 1109.04   569.6 1113.31   594.5 1142.86   629.3 1173.98   654.2 1190.38
   679.1 1199.31   738.9 1209.64   833.6 1214.89   873.4 1214.13   953.2 1207.49
   968.2 1202.69     998 1205.51  1047.9 1202.34  1082.8 1207.49  1152.6 1222.84
  1177.5 1223.35  1212.4 1228.56  1247.3 1225.48  1262.2  1226.7  1416.7 1266.61
#Mann= 3 , 0 , 0
       0      .1       0   531.9    .045       0   546.9      .1       0
Bank Sta=531.9,546.9
XS Rating Curve= 0 ,0
Exp/Cntr=0.3,0.1

Chan Stop Cuts=-1
Use User Specified Reach Order=0